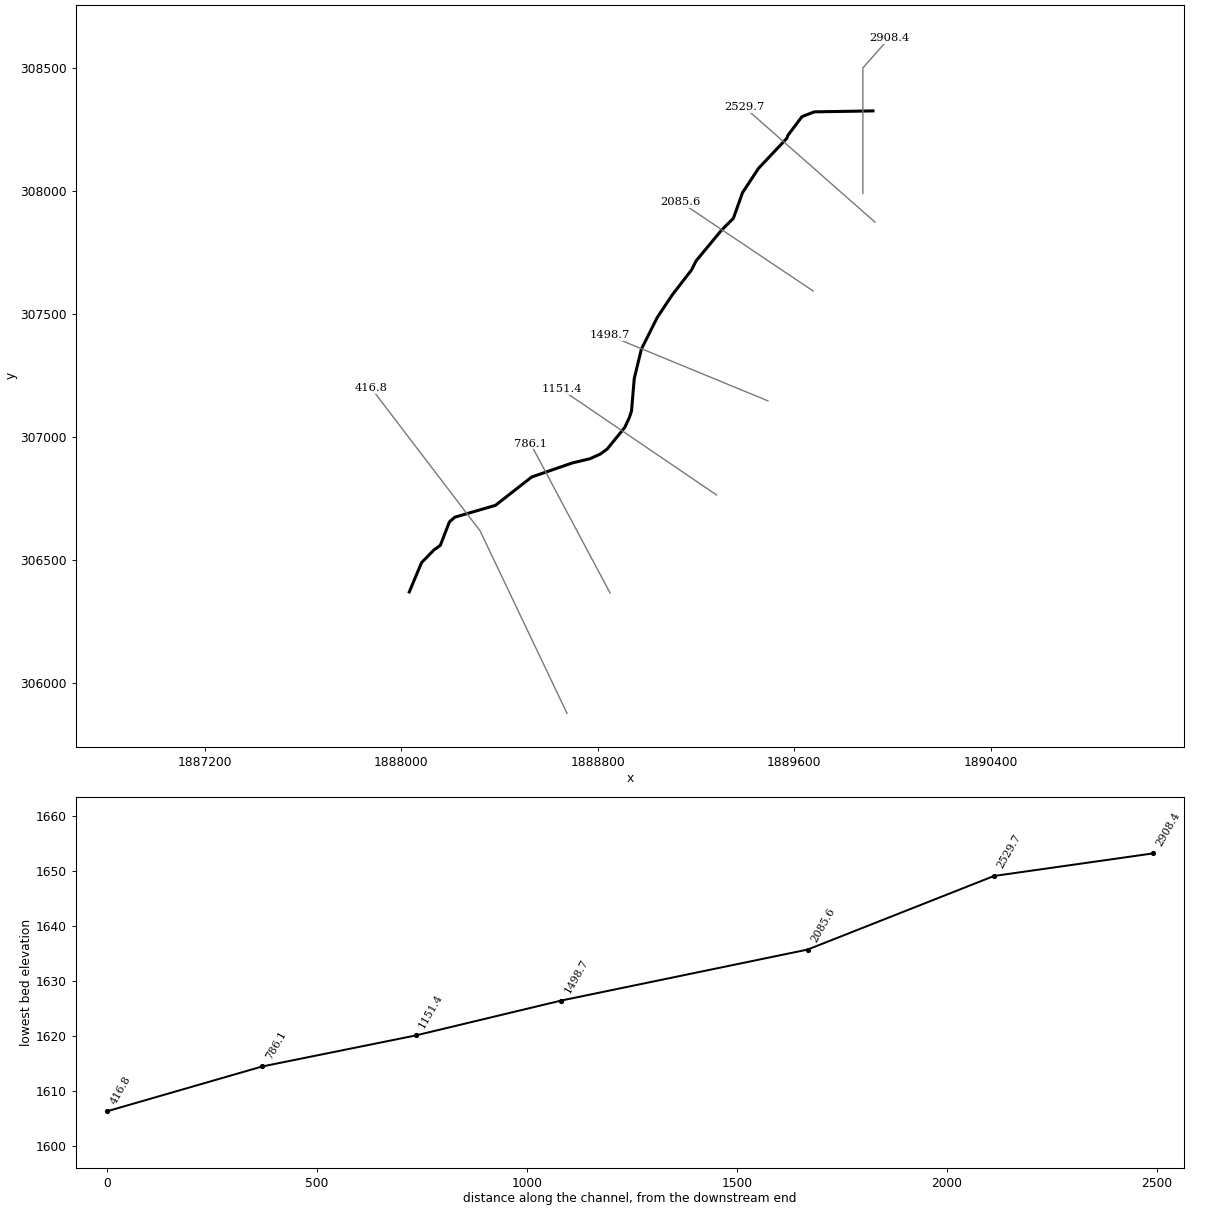
--- RFLISANCK.prj (project) ---

Proj Title=RFLISANCK
Current Plan=p01
Geom File=g01
Flow File=f01
Plan File=p01
DSS Export Rating Curves=0
DSS Export Rating Curve Sorted=0
DSS Export Volume Flow Curves=0
DXF OffsetX=0
DXF OffsetY=0
DXF ScaleX=0
DXF ScaleY=0

--- RFLISANCK.p01 (plan) ---

Plan Title=Floodplain
Program Version=4.00
Geom File=g01
Flow File=f01
K Sum by GR=0
Std Step Tol=0.01
Critical Tol=0.01
Num of Std Step Trials=20
Max Error Tol=0.3
Flow Tol Ratio=0.001
Split Flow NTrial=30
Split Flow Tol=0.02
Split Flow Ratio=0.02
Log Output Level=0
Friction Slope Method=1
Unsteady Friction Slope Method=2
Unsteady Bridges Friction Slope Method=1
Global Log Level=0
CheckData=False
Run HTab=0
Run UNet=0
Run PostProcess=0
UNET Theta=0
UNET Theta Warmup=0
UNET ZTol=0
UNET ZSATol=0
UNET MxIter=0
UNET MaxInSteps=0
UNET DtIC=0
UNET DtMin=0
UNET MaxCRTS=0
UNET WFStab=0
UNET SFStab=0
UNET WFX=0
UNET SFX=0
UNET DSS MLevel=0
UNET DZMax Abort=0
UNET Convert EG Bridges=0
UNET Use Existing IB Tables=0
UNET Froude Limit=0
UNET Froude Power=0
Write IC File=0
Echo Input=False
Echo Output=False
Write Detailed=0

--- RFLISANCK.f01 (steady flow) ---

Flow Title=NFF Regression Equation
Program Version=4.10
Number of Profiles= 1
Profile Names=P100yr
River Rch & RM=RFLISANCK,Main            ,2908.4
1064.916
Boundary for River Rch & Prof#=RFLISANCK,Main            , 1
Up Type= 0
Dn Type= 1
Dn Known WS=1610.15
DSS Import GetInterval= 0
DSS Import GetPeak= 0
DSS Import FillOption= 0

--- RFLISANCK.g01 (geometry) ---

Geom Title=USGS 10m DEM
Program Version=4.10

River Reach=RFLISANCK       ,Main
Reach XY= 30
     1889920.061      308326.548     1889681.266      308322.629
     1889631.112      308303.181     1889573.425      308226.605
     1889569.465       308214.85     1889454.246      308092.678
     1889389.142      307993.936     1889351.835      307889.271
     1889302.996      307840.432     1889200.152      307716.204
     1889181.824      307679.547     1889103.418      307578.129
     1889042.322      307486.485     1888977.542      307356.802
     1888948.604      307237.643     1888937.441      307105.657
     1888929.295        307080.2     1888909.948      307038.452
      1888838.67      306950.881     1888811.177      306930.516
     1888768.411      306911.169     1888696.114      306893.859
     1888531.156      306836.836     1888383.772      306721.498
     1888218.407      306673.321     1888196.272       306653.79
     1888159.381      306558.573     1888133.772      306540.248
     1888082.991      306488.165     1888033.182      306369.092

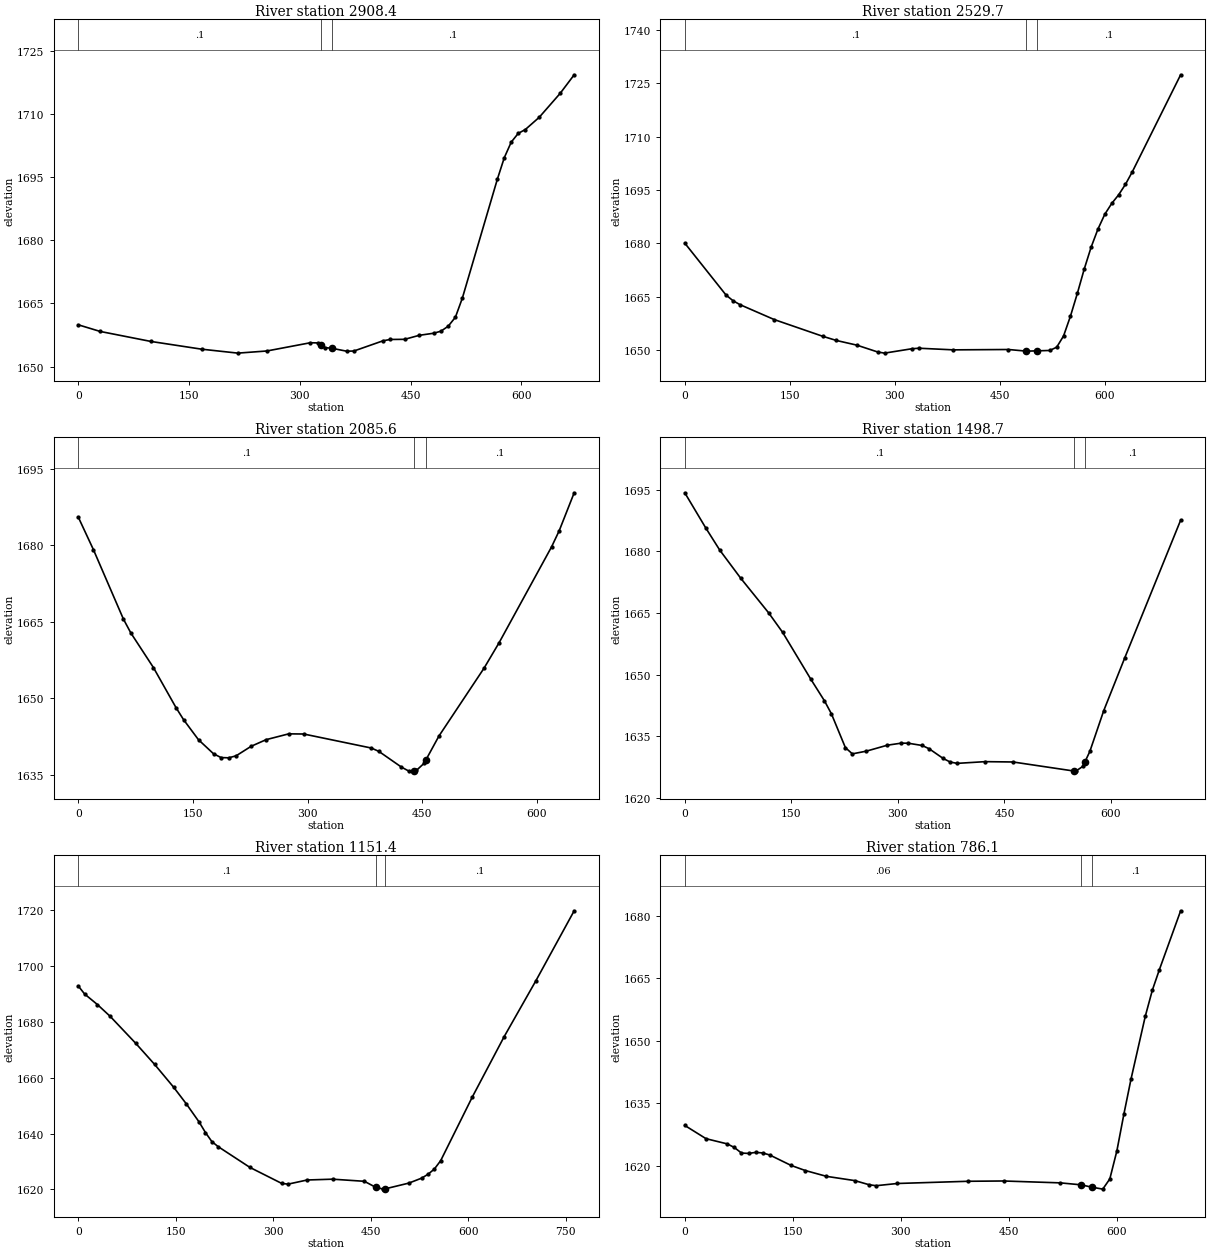
Type RM Length L Ch R = 1 ,2908.4  ,359.2,378.7,398.1
XS GIS Cut Line= 3
      1889878.83      307990.663      1889878.83      308501.242
     1889985.201      308621.795
#Sta/Elev= 30
       0 1659.91    29.5 1658.34    98.2 1655.96   166.9 1654.12     216 1653.18
   255.3 1653.69   314.2 1655.65     324 1655.61     329 1655.04   333.8  1654.5
     344 1654.31   363.3 1653.64   373.1 1653.68   412.4  1656.1   422.2 1656.43
   441.8 1656.46   461.5 1657.41   481.1 1657.91   490.9 1658.39   500.8 1659.57
   510.6 1661.72     520 1666.26   567.3 1694.48   576.8 1699.66   586.2 1703.36
   595.7 1705.44   605.2 1706.34   624.1 1709.26   652.4 1714.94   671.4 1719.36
#Mann= 3 , 0 , 0
       0      .1       0     329    .045       0     344      .1       0
Bank Sta=329,344
XS Rating Curve= 0 ,0
Exp/Cntr=0.3,0.1

Type RM Length L Ch R = 1 ,2529.7  ,441.2,444.1,447
XS GIS Cut Line= 2
      1889928.47      307873.656     1889396.617      308341.686
#Sta/Elev= 30
       0 1680.04      59 1665.41    68.9 1663.84    78.7 1662.74   127.9 1658.52
   196.8 1653.84   216.5 1652.65     246 1651.32   275.5 1649.41   285.4 1649.08
   324.7 1650.32   334.6 1650.46   383.8    1650   462.5  1650.1   488.1 1649.64
   503.1 1649.72   521.5 1649.83   531.4 1650.75   541.2  1653.9     551 1659.44
   560.9 1665.88   570.7 1672.71   580.6  1678.9   590.4 1684.02   600.2 1688.19
   610.1 1691.23   619.9 1693.64   629.7  1696.6   639.6 1700.18   708.5 1727.43
#Mann= 3 , 0 , 0
       0      .1       0   488.1    .045       0   503.1      .1       0
Bank Sta=488.1,503.1
XS Rating Curve= 0 ,0
Exp/Cntr=0.3,0.1

Type RM Length L Ch R = 1 ,2085.6  ,582.4,586.9,591.3
XS GIS Cut Line= 2
     1889676.726      307593.547     1889137.782      307955.206
#Sta/Elev= 30
       0  1685.5    19.7 1679.16      59 1665.53    68.8 1662.79    98.3 1656.02
   127.8 1648.18   137.7 1645.81   157.3 1641.86     177 1639.11   186.8 1638.37
   196.7 1638.32   206.5 1638.71   226.2 1640.58   245.8 1641.88   275.4 1643.02
     295 1642.99   383.5 1640.24   393.4 1639.58   422.9  1636.5   432.7 1635.71
   439.8 1635.81   442.5 1635.85   452.4 1637.22   454.8 1637.87     472 1642.59
     531 1655.89   550.7 1660.88   619.5 1679.71   629.4 1682.85     649 1690.29
#Mann= 3 , 0 , 0
       0      .1       0   439.8    .045       0   454.8      .1       0
Bank Sta=439.8,454.8
XS Rating Curve= 0 ,0
Exp/Cntr=0.3,0.1

Type RM Length L Ch R = 1 ,1498.7  ,351.8,347.3,342.5
XS GIS Cut Line= 2
     1889492.351       307146.79     1888847.036      307412.717
#Sta/Elev= 30
       0 1694.29    29.5 1685.73    49.2 1680.33    78.6  1673.5     118 1665.04
   137.6 1660.31     177 1648.97   196.6 1643.59   206.4 1640.42   226.1 1632.17
   235.9 1630.66   255.6 1631.32   285.1 1632.77   304.7 1633.27   314.6 1633.25
   334.2  1632.7   344.1 1631.89   363.7 1629.54   373.6 1628.67   383.4 1628.34
   422.7 1628.76     462 1628.68   548.3 1626.46   550.5 1626.45   560.3 1627.61
   563.3 1628.71   570.2 1631.25   589.8 1641.21   619.3 1654.04     698 1687.61
#Mann= 3 , 0 , 0
       0      .1       0   548.3    .045       0   563.3      .1       0
Bank Sta=548.3,563.3
XS Rating Curve= 0 ,0
Exp/Cntr=0.3,0.1

Type RM Length L Ch R = 1 ,1151.4  ,376.2,365.3,354.4
XS GIS Cut Line= 2
     1889283.155      306763.856     1888652.024      307192.884
#Sta/Elev= 30
       0 1692.77     9.8  1689.9    29.4 1686.15    48.9 1681.96    88.1 1672.35
   117.4 1664.74   146.8 1656.54   166.3 1650.59   185.9 1644.13   195.7 1640.34
   205.5 1637.13   215.2 1635.31   264.2 1627.86   313.1 1622.14   322.9 1621.89
   352.2 1623.37   391.4 1623.66   440.3  1622.9   457.6 1620.77   469.6  1620.1
   472.6 1620.22   508.8 1622.26   528.3 1624.02   538.1 1625.39   547.9 1627.26
   557.7 1630.27   606.6 1653.15   655.5 1674.69   704.4 1694.72   763.2  1719.7
#Mann= 3 , 0 , 0
       0      .1       0   457.6    .045       0   472.6      .1       0
Bank Sta=457.6,472.6
XS Rating Curve= 0 ,0
Exp/Cntr=0.3,0.1

Type RM Length L Ch R = 1 ,786.1   ,364.6,369.3,374
XS GIS Cut Line= 2
     1888850.369      306364.379     1888527.018      306972.018
#Sta/Elev= 30
       0 1629.72    29.5 1626.55      59  1625.3    68.8 1624.44    78.7 1623.11
    88.5 1623.02    98.3 1623.27   108.2 1623.14     118 1622.64   147.5 1620.15
   167.2 1618.93   196.7 1617.53     236 1616.51   255.7 1615.53   265.5 1615.29
     295 1615.82   393.3 1616.35   442.5 1616.42   521.2 1615.97   550.1  1615.5
   565.1 1614.94   580.2 1614.47     590 1616.91   599.8 1623.63   609.6 1632.49
   619.5 1640.88   639.2 1655.84     649 1662.09   658.8 1667.03   688.3 1681.12
#Mann= 3 , 0 , 0
       0     .06       0   550.1    .045       0   565.1      .1       0
Bank Sta=550.1,565.1
XS Rating Curve= 0 ,0
Exp/Cntr=0.3,0.1

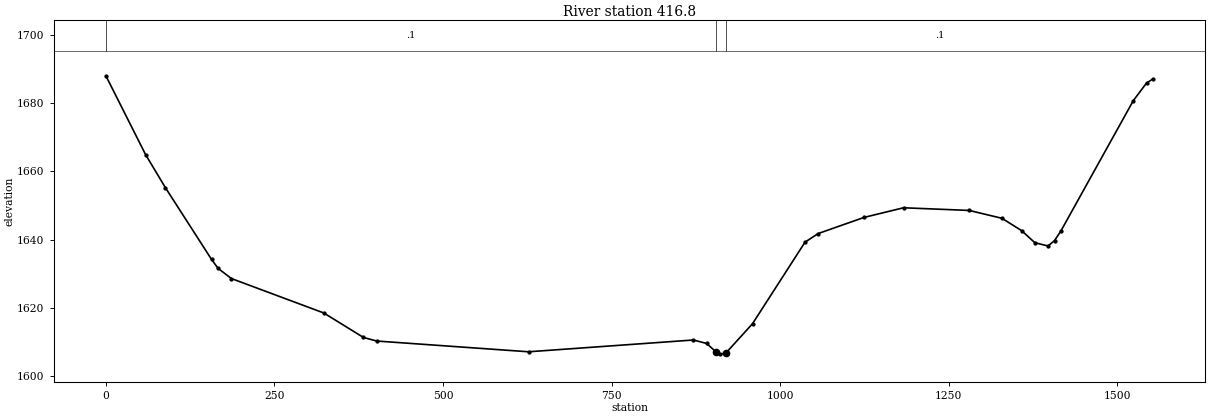
Type RM Length L Ch R = 1 ,416.8   ,404.3,416.8,429.3
XS GIS Cut Line= 3
        1888675.         305875.     1888321.182       306617.79
     1887878.039       307198.46
#Sta/Elev= 30
       0 1688.11    58.8 1664.99    88.2 1655.27   156.7 1634.16   166.5 1631.52
   186.1 1628.55   323.2 1618.43     382 1611.24   401.6 1610.19   626.9 1607.03
   871.4 1610.49   890.9 1609.48   904.4 1607.11   910.4 1606.34   919.4 1606.62
   959.1 1615.28    1037 1639.24  1056.5 1641.77  1124.7 1646.52  1183.1 1649.34
  1280.5 1648.56  1329.2 1646.24  1358.4  1642.6  1377.9 1639.07  1397.4 1638.12
  1407.1  1639.7  1416.8 1642.63    1524 1680.85  1543.5 1685.98  1553.2 1687.22
#Mann= 3 , 0 , 0
       0      .1       0   904.4    .045       0   919.4      .1       0
Bank Sta=904.4,919.4
XS Rating Curve= 0 ,0
Exp/Cntr=0.3,0.1

Chan Stop Cuts=-1
Use User Specified Reach Order=0
Composite Channel Slope=5